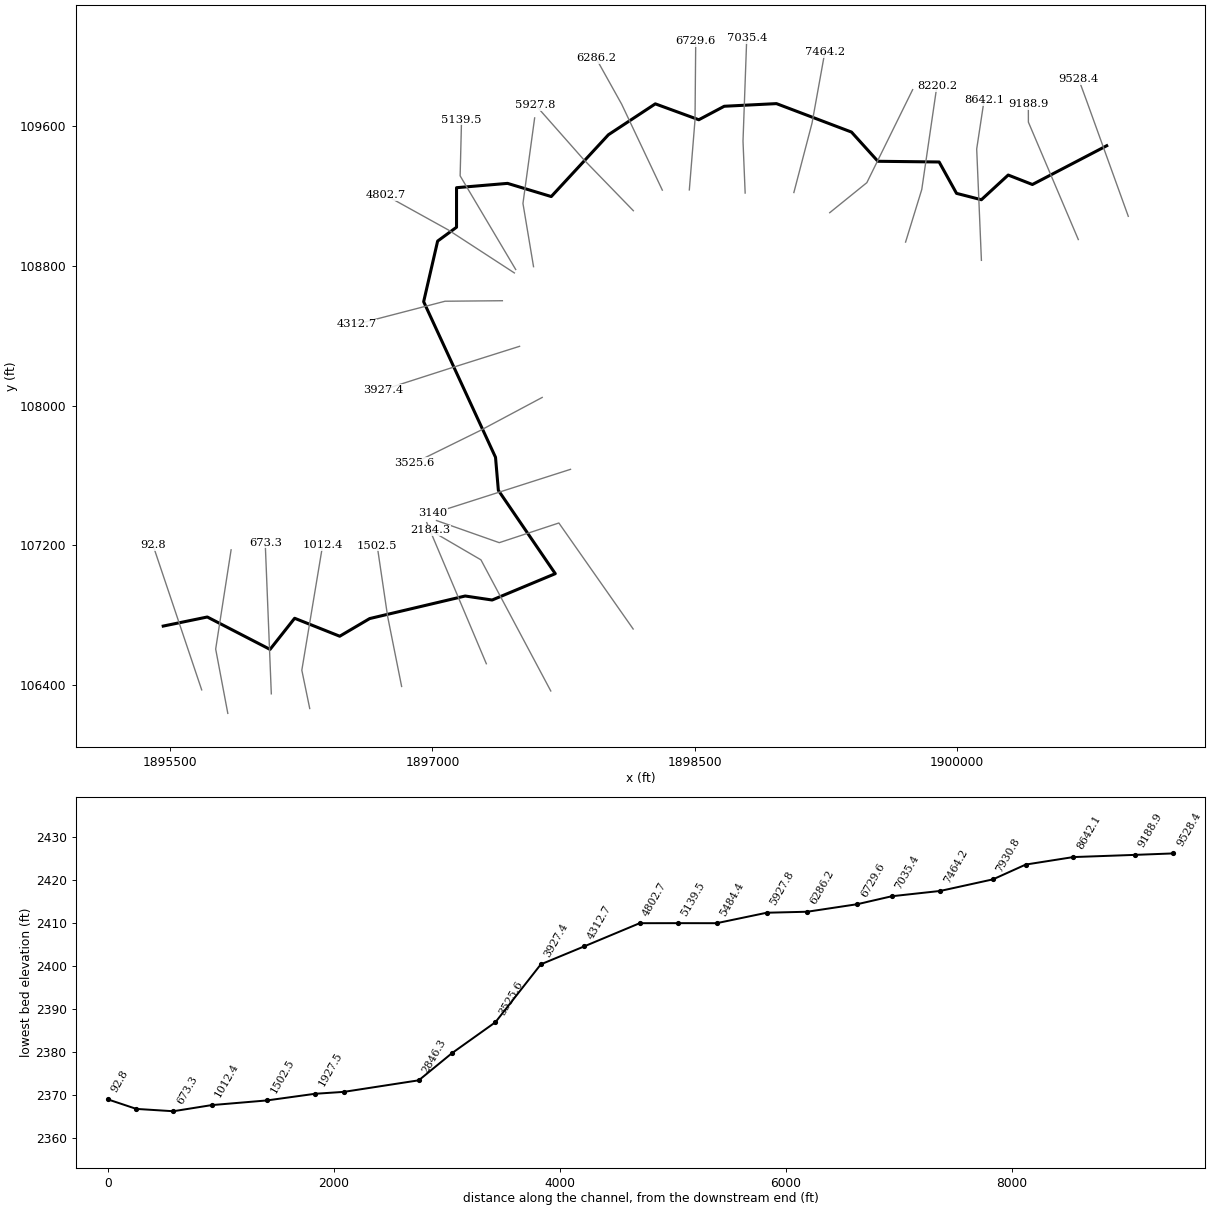
--- BrshFrk.prj (project) ---

Proj Title=BrshFrk
Current Plan=p01
Default Exp/Contr=0,0
English Units
Geom File=g01
Flow File=f01
Plan File=p01
BEGIN DESCRIPTION:
END DESCRIPTION:
DSS Export Rating Curves= 0
DSS Export Rating Curve Sorted= 0
DSS Export Volume Flow Curves= 0
DXF OffsetX= 0
DXF OffsetY= 0
DXF ScaleX= 0
DXF ScaleY= 0

--- BrshFrk.p01 (plan) ---

Plan Title=Floodplain
Program Version=4.00
Geom File=g01
Flow File=f01
K Sum by GR=0
Std Step Tol=0.01
Critical Tol=0.01
Num of Std Step Trials=20
Max Error Tol=0.3
Flow Tol Ratio=0.001
Split Flow NTrial=30
Split Flow Tol=0.02
Split Flow Ratio=0.02
Log Output Level=0
Friction Slope Method=1
Unsteady Friction Slope Method=2
Unsteady Bridges Friction Slope Method=1
Global Log Level=0
CheckData=False
Run HTab=0
Run UNet=0
Run PostProcess=0
UNET Theta=0
UNET Theta Warmup=0
UNET ZTol=0
UNET ZSATol=0
UNET MxIter=0
UNET MaxInSteps=0
UNET DtIC=0
UNET DtMin=0
UNET MaxCRTS=0
UNET WFStab=0
UNET SFStab=0
UNET WFX=0
UNET SFX=0
UNET DSS MLevel=0
UNET DZMax Abort=0
UNET Convert EG Bridges=0
UNET Use Existing IB Tables=0
UNET Froude Limit=0
UNET Froude Power=0
Write IC File=0
Echo Input=False
Echo Output=False
Write Detailed=0

--- BrshFrk.f01 (steady flow) ---

Flow Title=NFF Regression Equation
Program Version=4.10
Number of Profiles= 1
Profile Names=P100yr
River Rch & RM=BrshFrk,Main            ,9528.4
600.3024
River Rch & RM=BrshFrk,Main            ,5927.8
653.5281
River Rch & RM=BrshFrk,Main            ,5139.5
657.4269
River Rch & RM=BrshFrk,Main            ,1927.5
792.4283
Boundary for River Rch & Prof#=BrshFrk,Main            , 1
Up Type= 0
Dn Type= 1
Dn Known WS=2371
DSS Import GetInterval= 0
DSS Import GetPeak= 0
DSS Import FillOption= 0

--- BrshFrk.g01 (geometry) ---

Geom Title=USGS 3m DEM
Program Version=4.10

River Reach=BrshFrk         ,Main
Reach XY= 30
     1900855.717      109488.807     1900430.757      109266.623
     1900292.376      109320.938      1900139.09      109179.383
     1899996.948      109215.918     1899897.538       109395.71
     1899547.285      109399.738     1899396.295      109567.166
     1898967.215      109730.164     1898668.649       109715.02
     1898523.205      109637.716     1898274.507      109728.862
     1898006.278      109551.779     1897679.455      109197.612
     1897429.455      109273.133     1897137.788      109248.393
     1897137.788      109021.831     1897029.715      108942.404
     1896949.801       108595.05     1897360.725      107703.419
     1897376.979      107514.114     1897702.474       107036.55
     1897341.432      106885.583     1897187.149      106908.543
     1896641.244      106779.305     1896469.819      106678.081
     1896212.007      106780.945     1896071.382       106602.56
     1895712.669       106788.24     1895460.532      106736.221

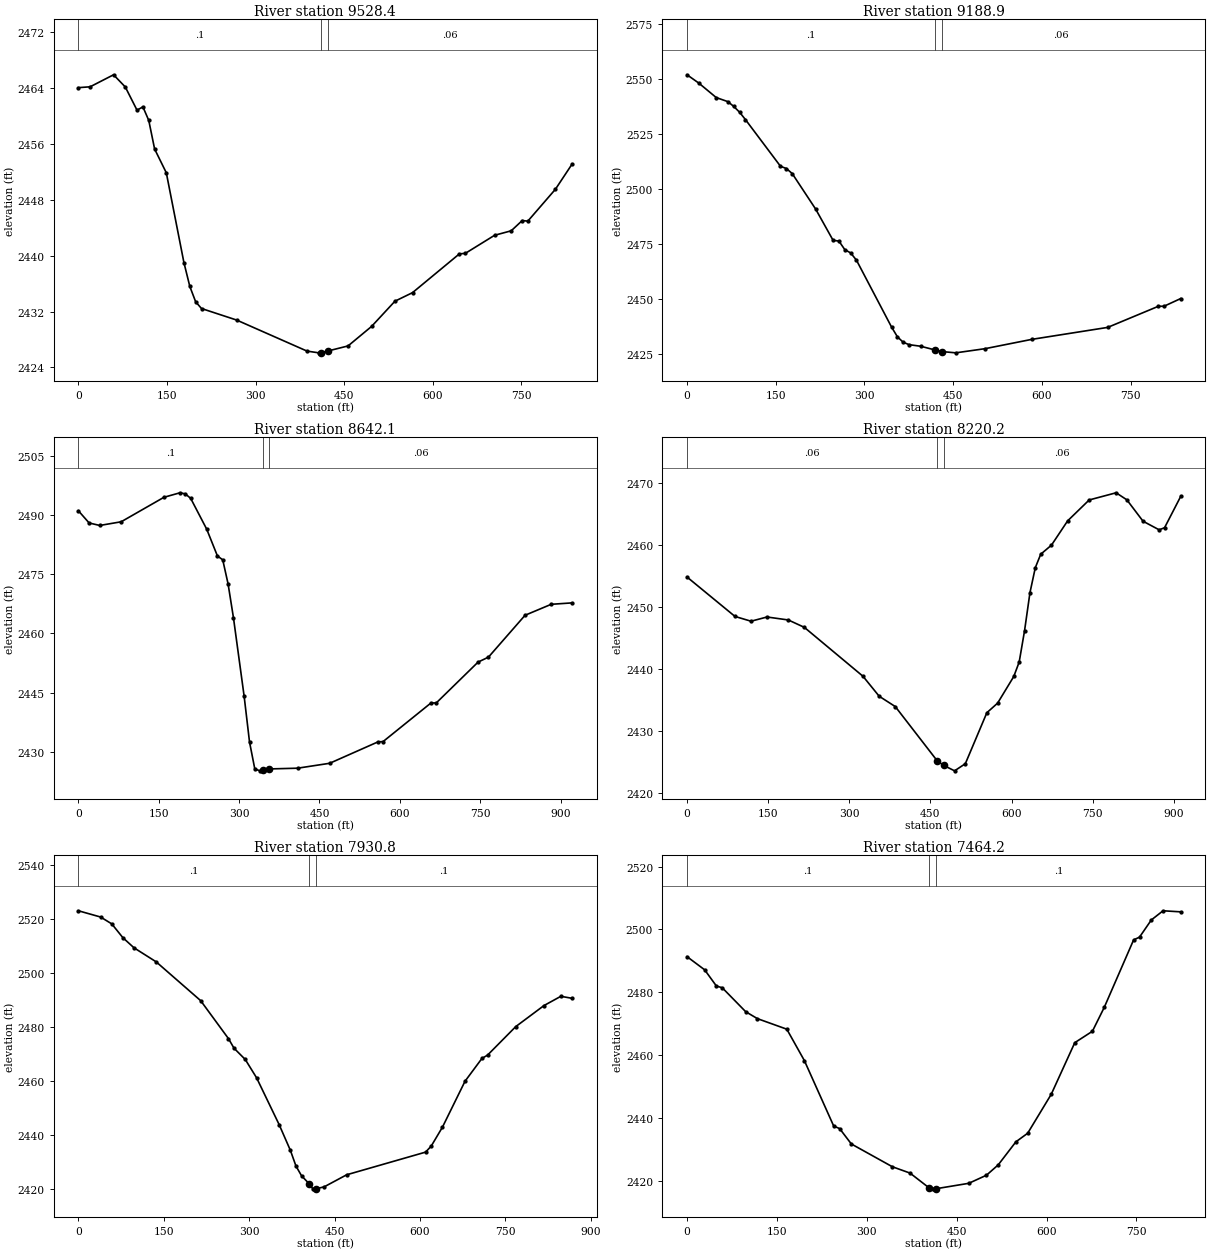
Type RM Length L Ch R = 1 ,9528.4  ,338.2,339.5,340.8
XS GIS Cut Line= 3
     1900979.085      109084.389      1900740.39      109747.288
      1900695.23      109870.452
#Sta/Elev= 30
       0 2464.03    19.8 2464.15    59.5 2465.87    79.4 2464.12    99.2 2460.81
   109.2 2461.28   119.1 2459.34     129 2455.25   148.8 2451.85   178.6 2439.01
   188.6 2435.59   198.5 2433.39   208.4 2432.43   267.9 2430.78     387 2426.34
   406.9 2426.09   410.6 2426.13   422.6 2426.36   456.5 2427.08   496.2 2429.86
   535.9 2433.48   565.6  2434.7     645 2440.25     655 2440.32   704.6 2442.91
   732.7 2443.55   751.4 2445.02   760.8 2444.93   807.6  2449.5   835.8  2453.1
#Mann= 3 , 0 , 0
       0      .1       0   410.6    .045       0   422.6     .06       0
Bank Sta=410.6,422.6
XS Rating Curve= 0 ,0
Exp/Cntr=0.3,0.1

Type RM Length L Ch R = 1 ,9188.9  ,555,546.8,537.8
XS GIS Cut Line= 3
      1900693.32      108951.298     1900407.849      109624.125
     1900407.578      109727.802
#Sta/Elev= 30
       0 2551.77    19.8 2548.02    49.4 2541.44    69.1 2539.59      79 2537.42
    88.9 2534.78    98.8 2531.44     158  2510.3   167.9 2509.29   177.8 2507.01
   217.3 2490.96   246.9 2476.74   256.8  2476.4   266.7 2472.52   276.6 2471.03
   286.4 2467.75   345.7 2437.46   355.6 2433.03   365.4 2430.55   375.3 2429.46
   395.1 2428.73   418.7 2427.09   430.7 2426.33   454.3 2425.75   503.7 2427.63
   582.7 2431.85   711.1 2437.28   796.9 2446.86   806.3 2446.86   834.6 2450.36
#Mann= 3 , 0 , 0
       0      .1       0   418.7    .045       0   430.7     .06       0
Bank Sta=418.7,430.7
XS Rating Curve= 0 ,0
Exp/Cntr=0.3,0.1

Type RM Length L Ch R = 1 ,8642.1  ,424.4,421.2,417.9
XS GIS Cut Line= 3
      1900139.25      108832.044     1900112.257      109470.171
     1900154.613      109749.897
#Sta/Elev= 30
       0 2491.04      20 2487.96    39.9 2487.33    79.8 2488.26   159.7 2494.46
   189.6  2495.6   199.6 2495.32   209.6 2494.18   239.5 2486.39   259.5 2479.61
   269.4 2478.64   279.4 2472.54   289.4    2464   309.4 2444.08   319.4 2432.55
   329.3 2425.69   339.3 2425.24   344.2 2425.48   356.2 2425.72   409.2 2425.91
     469 2427.15   558.9 2432.55   568.8 2432.65   658.2 2442.42     668 2442.42
     746 2452.75   765.5 2454.02   833.8 2464.61   882.6 2467.38   921.6 2467.74
#Mann= 3 , 0 , 0
       0      .1       0   344.2    .045       0   356.2     .06       0
Bank Sta=344.2,356.2
XS Rating Curve= 0 ,0
Exp/Cntr=0.3,0.1

Type RM Length L Ch R = 1 ,8220.2  ,296.1,289.4,282.7
XS GIS Cut Line= 3
     1899705.617      108936.667     1899798.191      109238.214
     1899884.405      109829.397
#Sta/Elev= 30
       0 2454.78    88.7 2448.42   118.3 2447.65   147.9 2448.33   187.3 2447.85
   216.9 2446.66   325.4 2438.76   355.3 2435.54   385.1 2433.87   462.6 2425.12
   474.6 2424.38   494.7  2423.5   514.6 2424.65   554.4 2432.88   574.3 2434.43
   604.2 2438.73   614.2 2441.07   624.1 2446.11   634.1 2452.26     644 2456.29
     654 2458.46   673.9 2459.93   703.8 2463.85   743.6 2467.22   793.4 2468.38
   813.3 2467.24   843.2 2463.79     873  2462.4     883 2462.74   912.9  2467.8
#Mann= 3 , 0 , 0
       0     .06       0   462.6    .045       0   474.6     .06       0
Bank Sta=462.6,474.6
XS Rating Curve= 0 ,0
Exp/Cntr=0.3,0.1

Type RM Length L Ch R = 1 ,7930.8  ,462.2,466.5,472.2
XS GIS Cut Line= 3
     1899271.831       109105.15     1899484.125      109277.215
      1899746.07      109810.257
#Sta/Elev= 30
       0 2523.15      39 2520.83    58.6 2518.29    78.1 2513.17    97.6 2509.43
   136.6 2504.22   214.7 2489.84   263.5 2475.78   273.3 2472.21   293.1 2468.02
   312.9 2461.26   352.5 2443.92   372.3 2434.36   382.2 2428.49     392 2424.89
   405.8 2421.86   411.8 2420.07   417.8 2420.12   431.6  2420.8   471.2 2425.28
   609.8 2433.68   619.7 2435.91   639.5 2442.96   679.1 2459.96   708.8 2468.41
   718.7 2469.65   768.2 2480.21   817.7    2488   847.4 2491.44   867.2  2490.7
#Mann= 3 , 0 , 0
       0      .1       0   405.8    .045       0   417.8      .1       0
Bank Sta=405.8,417.8
XS Rating Curve= 0 ,0
Exp/Cntr=0.3,0.1

Type RM Length L Ch R = 1 ,7464.2  ,423.1,428.8,432.8
XS GIS Cut Line= 3
     1899066.836      109220.685     1899170.689      109618.613
     1899243.786      110024.747
#Sta/Elev= 30
       0 2491.32    29.4 2487.13      49 2481.97    58.8 2481.41    97.9 2473.79
   117.5 2471.58   166.5 2468.22   195.8 2458.23   244.8 2437.36   254.6 2436.58
   274.2 2431.67   342.7 2424.41   372.1  2422.4   404.3 2417.64   411.3 2417.38
   416.3 2417.44   470.2 2419.14   499.7 2421.72   519.3 2425.01   548.8 2432.35
   568.5 2435.09   607.8 2447.49   647.1 2463.93   676.5 2467.56   696.2 2475.14
   745.3 2496.67   755.1 2497.53   774.8    2503   794.4 2505.93   823.9 2505.59
#Mann= 3 , 0 , 0
       0      .1       0   404.3    .045       0   416.3      .1       0
Bank Sta=404.3,416.3
XS Rating Curve= 0 ,0
Exp/Cntr=0.3,0.1

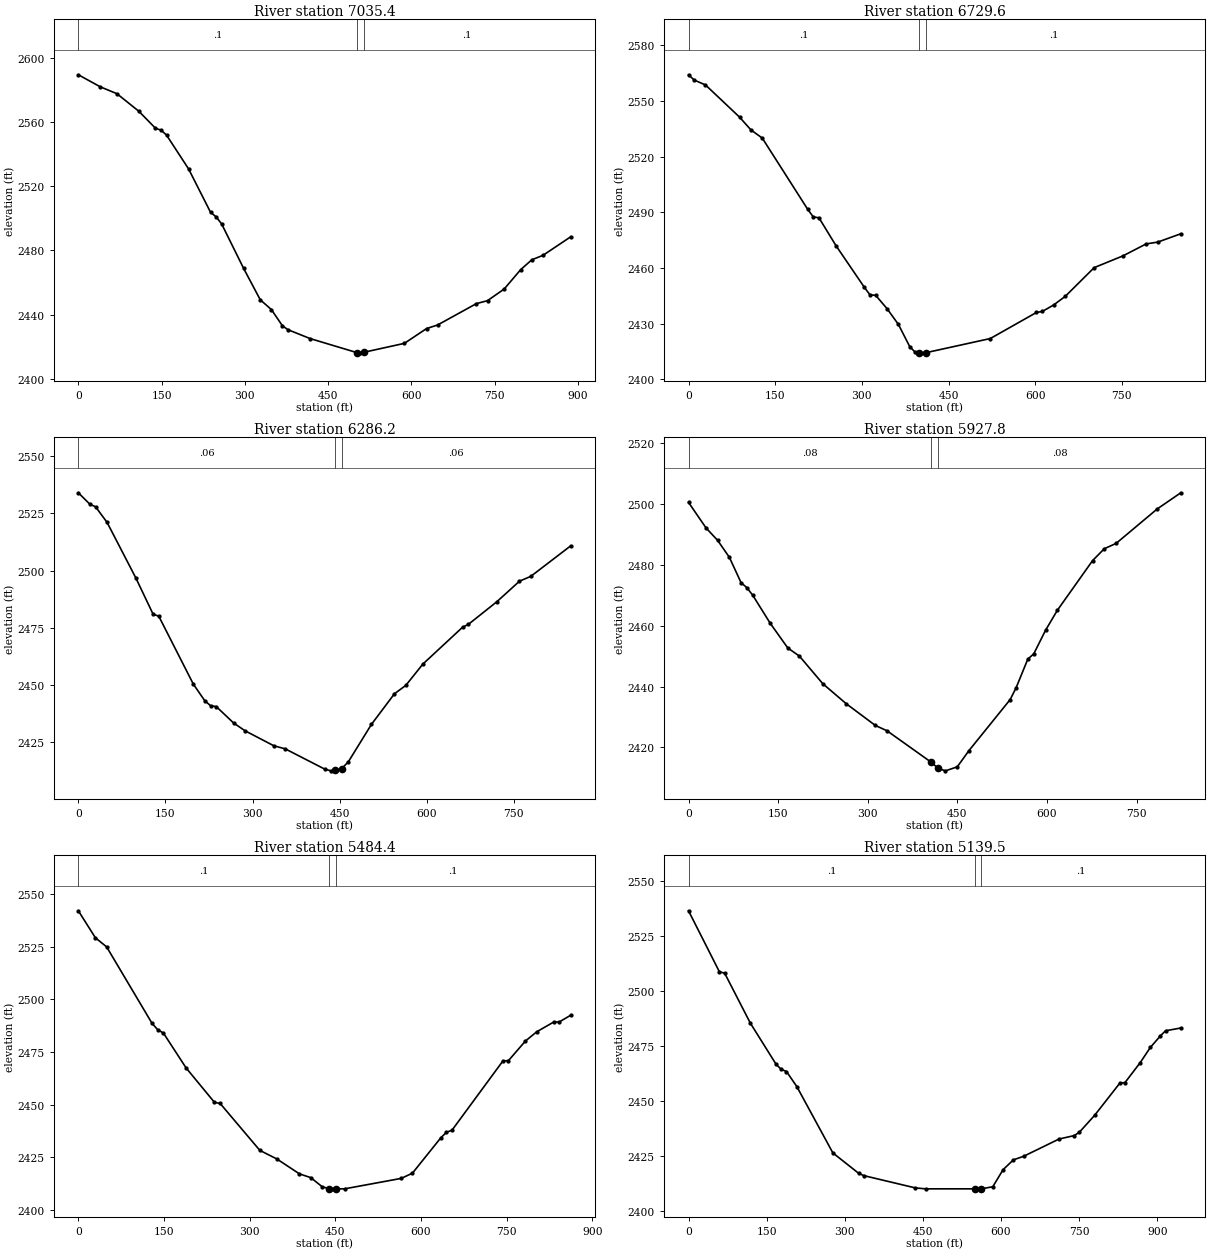
Type RM Length L Ch R = 1 ,7035.4  ,306.9,305.9,306.1
XS GIS Cut Line= 3
     1898788.252      109217.686     1898775.936      109515.331
      1898797.24      110104.274
#Sta/Elev= 30
       0 2589.42    39.7 2581.89    69.5 2577.63   109.2 2566.64     139 2556.09
     149 2554.93   158.9 2551.85   198.6  2530.8   238.3  2503.7   248.2 2500.93
   258.2 2496.51   297.9 2468.74   327.9 2449.18   347.8 2443.15   367.8    2433
   377.8 2430.56   417.8 2425.03   502.3 2416.26   507.7 2416.15   514.3 2416.48
   587.6 2422.06   627.5 2431.28   647.5 2433.51   717.4 2446.83   737.4 2448.66
   767.4 2455.91   797.3 2468.03   817.3 2474.16   837.3 2476.89   887.2 2488.43
#Mann= 3 , 0 , 0
       0      .1       0   502.3    .045       0   514.3      .1       0
Bank Sta=502.3,514.3
XS Rating Curve= 0 ,0
Exp/Cntr=0.3,0.1

Type RM Length L Ch R = 1 ,6729.6  ,432.1,443.1,452.9
XS GIS Cut Line= 3
     1898468.998      109235.763     1898501.521      109636.885
     1898505.604       110086.38
#Sta/Elev= 30
       0 2564.08     9.8 2561.25    29.4  2558.6    88.3 2541.28     108 2534.38
   127.6    2530   206.1  2491.7   215.9 2487.52   225.8 2487.04   255.2 2472.05
   304.3  2449.6   314.1 2445.51   323.9  2445.3   343.6 2438.09   363.2 2429.64
   382.8 2417.69   392.6 2414.54     399 2414.38   402.4  2414.3     411 2414.39
   522.3    2422   602.2 2436.05   612.2 2436.58   632.2 2440.13   652.2 2444.78
   702.1  2460.2   752.1 2466.56     792 2472.97     812 2473.94     852 2478.44
#Mann= 3 , 0 , 0
       0      .1       0     399    .045       0     411      .1       0
Bank Sta=399,411
XS Rating Curve= 0 ,0
Exp/Cntr=0.3,0.1

Type RM Length L Ch R = 1 ,6286.2  ,351.3,358.3,364.3
XS GIS Cut Line= 3
     1898314.549      109234.455     1898082.117      109726.761
     1897934.583      109991.975
#Sta/Elev= 30
       0 2533.95    19.8 2528.97    29.7 2527.83    49.5 2521.01      99 2496.78
   128.7 2480.97   138.6 2480.04     198 2450.43   217.8 2443.14   227.7    2441
   237.6 2440.59   267.3 2433.47   287.1 2430.04   336.6 2423.51   356.4 2422.14
   425.6 2413.14   435.5 2412.55   441.3 2412.81   453.3 2413.41   465.2 2416.56
   504.8 2432.83   544.4 2446.19     564 2449.85   593.4 2459.16   661.9 2475.28
   671.7 2476.48   720.6 2486.34   759.8 2495.35   779.4 2497.48   847.9 2510.76
#Mann= 3 , 0 , 0
       0     .06       0   441.3    .045       0   453.3     .06       0
Bank Sta=441.3,453.3
XS Rating Curve= 0 ,0
Exp/Cntr=0.3,0.1

Type RM Length L Ch R = 1 ,5927.8  ,463,443.7,425.3
XS GIS Cut Line= 3
     1898148.854      109116.547     1897863.351      109411.301
     1897590.035       109721.46
#Sta/Elev= 30
       0 2500.47    29.3 2492.09    48.8 2487.98    68.4 2482.42    87.9 2474.12
    97.7 2472.45   107.5 2469.97   136.8 2460.75   166.1 2452.67   185.6 2449.99
   224.7 2440.93   263.8 2434.38   312.6 2427.23   332.2 2425.47     406 2415.16
     418  2413.1     430 2412.32   449.7 2413.63   469.4 2418.99   538.3 2435.73
   548.2 2439.59   567.8 2449.02   577.7 2450.71   597.4 2458.45   617.1    2465
   676.1 2481.33   695.8 2485.26   715.5 2486.99   784.4 2498.32   823.8 2503.62
#Mann= 3 , 0 , 0
       0     .08       0     406    .045       0     418     .08       0
Bank Sta=406,418
XS Rating Curve= 0 ,0
Exp/Cntr=0.3,0.1

Type RM Length L Ch R = 1 ,5484.4  ,329,344.1,359.2
XS GIS Cut Line= 3
     1897578.163      108795.741     1897517.618      109158.158
     1897584.488      109648.149
#Sta/Elev= 30
       0 2542.16    29.8 2529.34    49.6 2524.96   129.1 2488.59     139 2485.58
     149 2483.98   188.7  2467.4   238.3 2451.04   248.3  2450.5   317.8 2428.18
   347.6  2424.1   387.2    2417     407 2415.22   426.8 2410.93   438.4 2409.96
   446.6 2409.89   450.4 2409.89   466.4  2409.9   565.2 2414.85     585 2417.34
   634.5 2434.11   644.4 2436.75   654.3  2437.8   743.3 2470.68   753.2  2470.9
   782.8 2480.19   802.6 2484.59   832.3 2489.23   842.2 2489.29     862 2492.46
#Mann= 3 , 0 , 0
       0      .1       0   438.4    .045       0   450.4      .1       0
Bank Sta=438.4,450.4
XS Rating Curve= 0 ,0
Exp/Cntr=0.3,0.1

Type RM Length L Ch R = 1 ,5139.5  ,328.2,337,345.9
XS GIS Cut Line= 3
     1897476.166       108779.48     1897158.392      109316.217
     1897166.452      109637.511
#Sta/Elev= 30
       0  2536.4    59.4  2508.6    69.3 2508.06   118.8 2485.25   168.3 2466.51
   178.2 2464.23   188.1 2463.28   207.9 2456.45   277.2 2426.23   326.7 2416.97
   336.6 2415.91   435.6 2410.32   455.4  2409.9   549.6  2409.9   561.6  2409.9
   584.2 2410.84     604 2418.63   623.8 2423.09   643.2 2424.68   711.4 2432.56
   740.6 2434.13   750.4 2435.64   779.6  2443.3   828.3 2458.04     838 2458.23
   867.2 2467.29   886.7 2474.22   906.2 2479.53   915.9 2481.81   945.2 2483.07
#Mann= 3 , 0 , 0
       0      .1       0   549.6    .045       0   561.6      .1       0
Bank Sta=549.6,561.6
XS Rating Curve= 0 ,0
Exp/Cntr=0.3,0.1

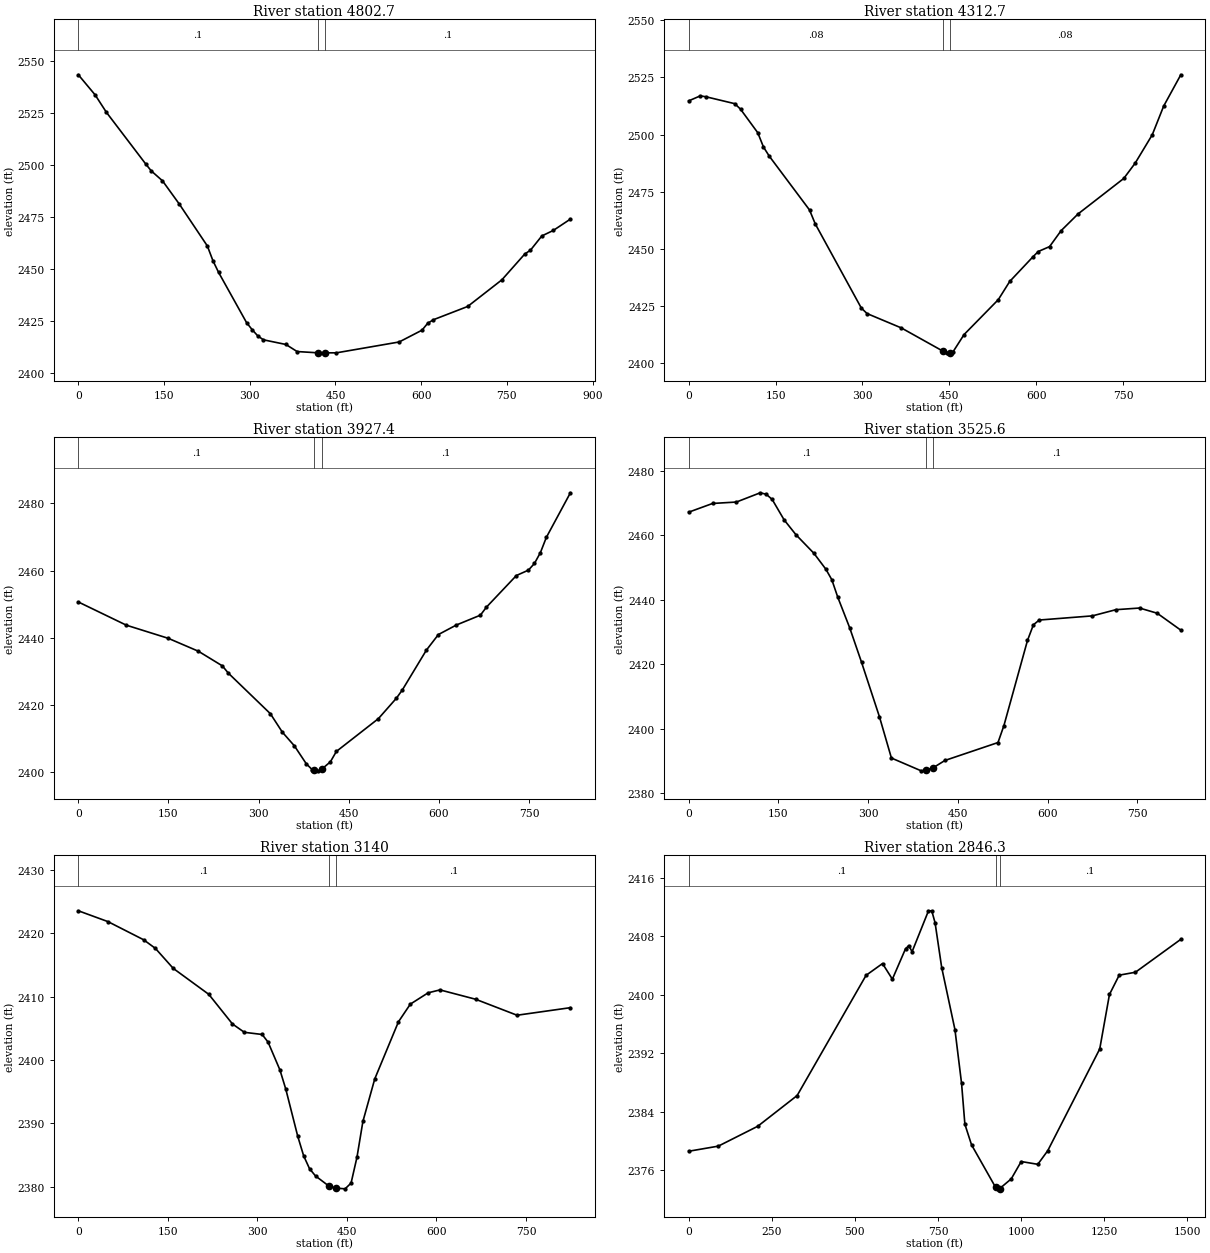
Type RM Length L Ch R = 1 ,4802.7  ,471.5,489.7,507.9
XS GIS Cut Line= 3
     1897468.557      108759.884     1897090.266      109006.567
     1896732.139      109205.292
#Sta/Elev= 30
       0  2543.2    29.4 2533.56    49.1 2525.22   117.8 2500.48   127.6 2497.13
   147.3 2492.36   176.7 2481.22   225.8 2461.13   235.6 2454.05   245.4 2448.49
   294.5 2424.34   304.4 2420.94   314.2 2417.97     324 2416.13   363.3  2413.9
   382.9 2410.51   419.4  2409.9   431.4  2409.9   451.6 2409.89   561.5  2415.1
   601.5 2420.76   611.4 2424.05   621.4 2425.76   681.4 2432.12   741.3  2444.9
   781.3 2457.26   791.3  2459.1   811.2 2465.94   831.2 2468.56   861.2 2474.01
#Mann= 3 , 0 , 0
       0      .1       0   419.4    .045       0   431.4      .1       0
Bank Sta=419.4,431.4
XS Rating Curve= 0 ,0
Exp/Cntr=0.3,0.1

Type RM Length L Ch R = 1 ,4312.7  ,384,385.1,386.2
XS GIS Cut Line= 3
      1897399.94      108600.664     1897072.178      108597.765
     1896566.983      108466.357
#Sta/Elev= 30
       0 2514.73    19.9  2516.9    29.8 2516.51    79.5 2513.49    89.4  2511.1
   119.2 2500.79   129.1 2494.52   139.1 2490.53   208.6    2467   218.5 2460.91
     298 2424.13   307.9  2421.7   367.2 2415.41     439 2405.26     446 2404.52
     451 2404.62   455.8 2404.72   475.5 2412.52   534.6 2427.78   554.3 2435.73
   593.7 2446.32   603.6 2448.83   623.2 2450.99     643 2457.93   672.5  2465.3
   751.3 2480.79     771 2487.49   800.5 2499.89   820.2 2512.44   849.8 2526.13
#Mann= 3 , 0 , 0
       0     .08       0     439    .045       0     451     .08       0
Bank Sta=439,451
XS Rating Curve= 0 ,0
Exp/Cntr=0.3,0.1

Type RM Length L Ch R = 1 ,3927.4  ,397.8,401.7,405
XS GIS Cut Line= 3
     1897498.219      108339.367     1897107.803      108215.817
     1896718.062      108090.125
#Sta/Elev= 30
       0 2450.63    79.9 2443.72   149.8  2439.8   199.8 2435.96   239.7  2431.6
   249.7 2429.43   319.6 2417.36   339.6 2411.85   359.6 2407.78   379.5 2402.42
   389.5 2400.65   392.8 2400.55   399.5 2400.34   404.8 2400.79   419.5 2403.02
   429.5 2406.12   499.4 2415.88   529.4 2421.97   539.3 2424.44   579.3 2436.29
   599.3 2440.93   629.2 2443.77   669.2  2446.7   679.2 2449.08   729.1 2458.51
   749.1 2460.11   759.1 2462.09   769.1 2465.34     779 2469.88     819 2483.15
#Mann= 3 , 0 , 0
       0      .1       0   392.8    .045       0   404.8      .1       0
Bank Sta=392.8,404.8
XS Rating Curve= 0 ,0
Exp/Cntr=0.3,0.1

Type RM Length L Ch R = 1 ,3525.6  ,389.6,385.4,381.8
XS GIS Cut Line= 3
     1897627.682      108046.468      1897267.29      107853.835
     1896895.884      107670.625
#Sta/Elev= 30
       0  2467.1    39.9  2469.8    79.7 2470.24   119.6 2473.11   129.6 2472.65
   139.5 2471.05   159.5 2464.71   179.4 2460.08   209.3 2454.35   229.2 2449.44
   239.2 2446.18   249.2 2440.74   269.1 2431.27     289 2420.54   318.9 2403.66
   338.9 2390.88   388.7 2386.91   396.5 2387.13   408.5 2387.84   428.4 2390.13
   517.1 2395.68     527 2400.93   566.4 2427.32   576.3 2432.18   586.1 2433.66
   674.9 2434.95   714.3 2436.87   753.8 2437.38   783.3 2435.77   822.8 2430.52
#Mann= 3 , 0 , 0
       0      .1       0   396.5    .045       0   408.5      .1       0
Bank Sta=396.5,408.5
XS Rating Curve= 0 ,0
Exp/Cntr=0.3,0.1

Type RM Length L Ch R = 1 ,3140    ,294.4,293.1,291.9
XS GIS Cut Line= 2
     1897789.559      107634.452     1897004.438      107382.554
#Sta/Elev= 30
       0  2423.5    49.7 2421.79   109.3 2418.94   129.1 2417.58     159 2414.43
   218.6 2410.34   258.3 2405.67   278.2 2404.36     308 2404.02   317.9 2402.82
   337.8 2398.43   347.7 2395.38   367.6    2388   377.5 2384.92   387.4 2382.88
   397.4 2381.74   420.5  2380.1   432.5 2379.82     447 2379.71     457 2380.62
   466.9  2384.7   476.8 2390.32   496.7 2397.03   536.4 2406.02   556.3  2408.8
   586.1 2410.58     606 2411.04   665.6 2409.57   735.1 2407.05   824.5 2408.24
#Mann= 3 , 0 , 0
       0      .1       0   420.5    .045       0   432.5      .1       0
Bank Sta=420.5,432.5
XS Rating Curve= 0 ,0
Exp/Cntr=0.3,0.1

Type RM Length L Ch R = 1 ,2846.3  ,693.4,661.9,629.7
XS GIS Cut Line= 4
     1898147.804      106719.526     1897722.948      107326.958
     1897382.139      107214.231     1897023.315      107340.947
#Sta/Elev= 30
       0 2378.57      89 2379.27   207.6 2381.99   326.2  2386.2   533.7 2402.67
   583.1 2404.28   612.8 2402.14   652.3  2406.3   662.2 2406.74   672.1  2405.9
   721.5 2411.51   731.4 2411.49   741.3 2409.87   761.2 2403.74   801.1 2395.23
     821 2387.87     831 2382.27     851 2379.45   923.6 2373.61   930.7 2373.42
   935.6 2373.45   970.6 2374.79  1000.5 2377.16  1050.4 2376.78  1080.3 2378.64
  1236.8 2392.58  1266.1 2400.05  1295.4 2402.69  1344.2 2403.09  1480.8  2407.6
#Mann= 3 , 0 , 0
       0      .1       0   923.6    .045       0   935.6      .1       0
Bank Sta=923.6,935.6
XS Rating Curve= 0 ,0
Exp/Cntr=0.3,0.1

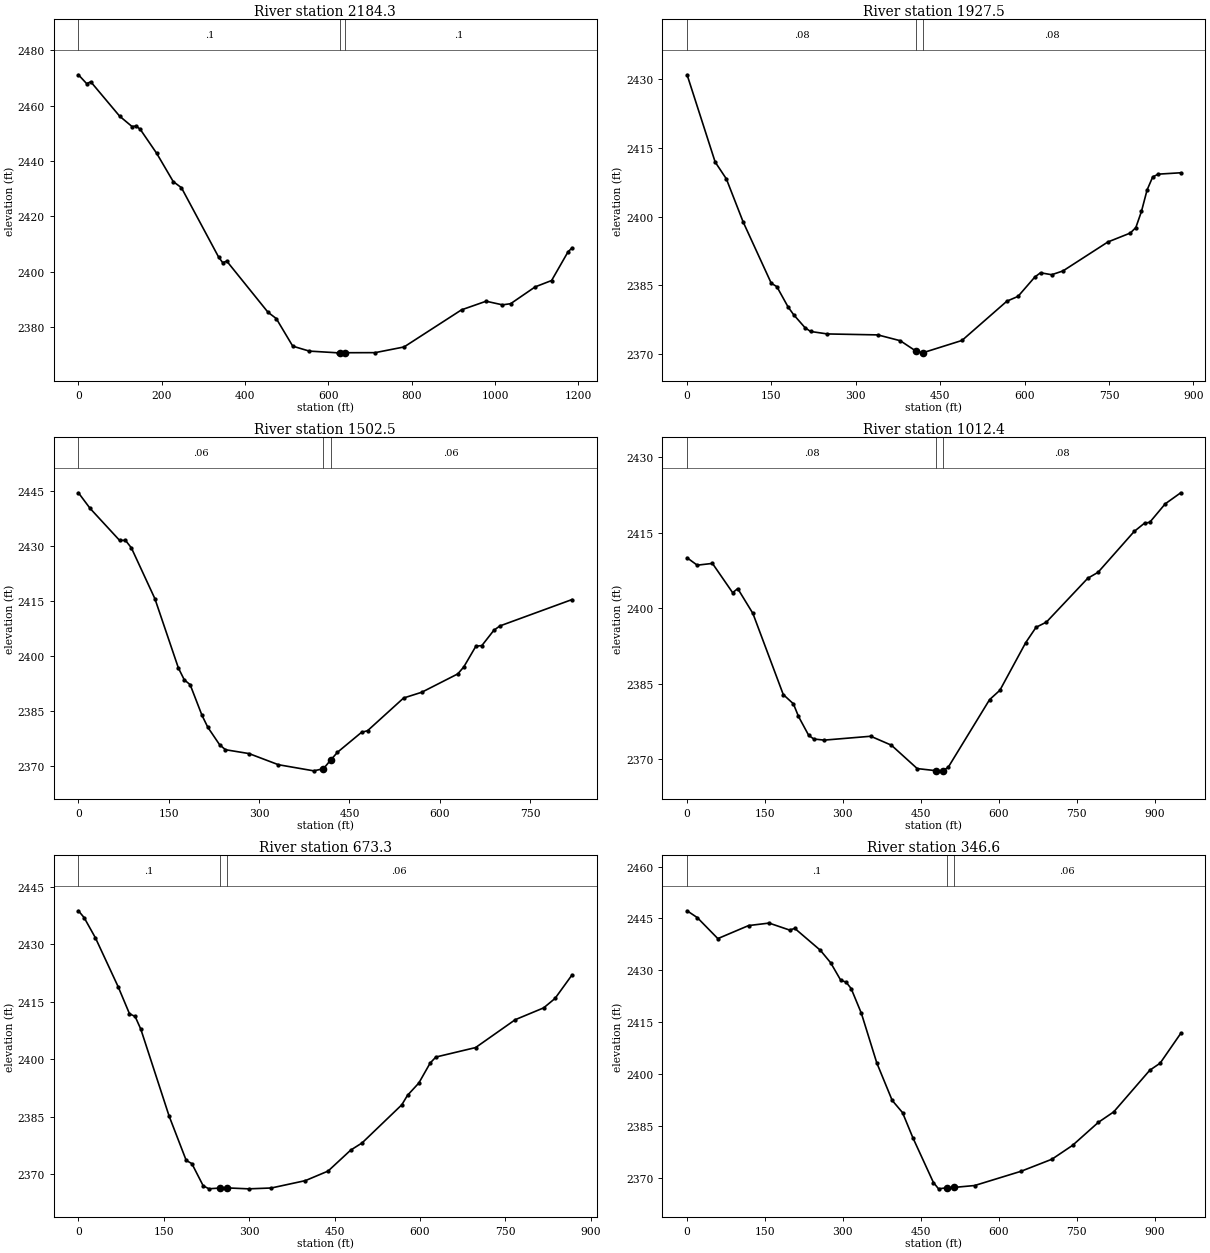
Type RM Length L Ch R = 1 ,2184.3  ,258.8,256.7,254.4
XS GIS Cut Line= 3
     1897676.681      106364.345      1897277.45      107115.701
     1896989.039      107284.313
#Sta/Elev= 30
       0  2471.1    19.8 2467.91    29.7 2468.57    98.9 2456.17   128.6 2452.43
   138.5 2452.61   148.4 2451.42     188 2442.72   227.6 2432.55   247.3 2430.34
   336.4 2405.34   346.3  2403.3   356.2 2403.83   455.1 2385.38   474.9 2383.12
   514.5 2373.15     554 2371.37   623.3 2370.74   628.6 2370.74   640.6 2370.78
   712.3 2370.81   781.6 2372.86   919.6 2386.26   978.6 2389.37  1017.9 2388.06
  1037.5 2388.48  1096.5 2394.56  1135.8 2396.84  1175.1 2407.16  1184.9 2408.64
#Mann= 3 , 0 , 0
       0      .1       0   628.6    .045       0   640.6      .1       0
Bank Sta=628.6,640.6
XS Rating Curve= 0 ,0
Exp/Cntr=0.3,0.1

Type RM Length L Ch R = 1 ,1927.5  ,429.2,425,419.9
XS GIS Cut Line= 2
     1897308.241      106520.412     1896967.489      107329.184
#Sta/Elev= 30
       0  2430.9    49.9 2411.88    69.8 2408.21    99.7 2398.81   149.6 2385.47
   159.6 2384.71   179.5  2380.3   189.5 2378.59   209.4 2375.81   219.4 2374.95
   249.3 2374.41   339.1  2374.2     379 2372.93   406.7 2370.68   418.7 2370.29
   488.7 2372.99   568.5 2381.55   588.4  2382.6   618.3 2386.83   628.3 2387.74
   648.2 2387.32   668.2 2388.14     748 2394.45   787.9  2396.4   797.8  2397.6
   807.8 2401.13   817.8  2405.8   827.8 2408.64   837.7 2409.24   877.6 2409.54
#Mann= 3 , 0 , 0
       0     .08       0   406.7    .045       0   418.7     .08       0
Bank Sta=406.7,418.7
XS Rating Curve= 0 ,0
Exp/Cntr=0.3,0.1

Type RM Length L Ch R = 1 ,1502.5  ,498.2,490.6,483.9
XS GIS Cut Line= 3
     1896823.828      106390.188     1896743.629      106792.405
     1896683.944      107197.419
#Sta/Elev= 30
       0 2444.59    19.5 2440.31    68.4  2431.6    78.1 2431.62    87.9 2429.57
     127 2415.69     166 2396.79   175.8 2393.56   185.5 2392.25   205.1 2383.91
   214.8 2380.64   234.4 2375.87   244.1 2374.51   283.2 2373.46     332 2370.42
   390.6 2368.75   406.7 2369.32   418.7 2371.67   430.1 2373.82     470 2379.25
     480 2379.69   539.9 2388.62   569.9 2390.18   629.8 2395.19   639.8  2397.1
   659.8 2402.73   669.8 2402.92   689.7 2407.09   699.7 2408.27   819.5 2415.47
#Mann= 3 , 0 , 0
       0     .06       0   406.7    .045       0   418.7     .06       0
Bank Sta=406.7,418.7
XS Rating Curve= 0 ,0
Exp/Cntr=0.3,0.1

Type RM Length L Ch R = 1 ,1012.4  ,334.8,338.4,336.3
XS GIS Cut Line= 3
     1896298.302      106263.822     1896253.142      106483.463
       1896372.2      107199.862
#Sta/Elev= 30
       0 2410.04    19.5 2408.57    48.8 2408.92    87.7  2403.1    97.5 2403.91
   126.7 2398.97   185.2 2382.83   204.7 2380.99   214.5 2378.48   234.2 2374.71
   244.1 2373.99     264 2373.77   353.6 2374.54   393.4 2372.76   443.1 2368.11
   480.2 2367.68   492.2 2367.66   502.8 2368.37   582.4 2381.82   602.3 2383.69
     652 2393.16   671.9 2396.21   691.8 2397.24   771.4 2405.96   791.3 2407.15
   860.9 2415.28   880.8 2416.93   890.8 2417.09   920.6 2420.77   950.5 2422.97
#Mann= 3 , 0 , 0
       0     .08       0   480.2    .045       0   492.2     .08       0
Bank Sta=480.2,492.2
XS Rating Curve= 0 ,0
Exp/Cntr=0.3,0.1

Type RM Length L Ch R = 1 ,673.3   ,331,326.8,328.5
XS GIS Cut Line= 2
     1896078.661      106347.983     1896043.765      107214.231
#Sta/Elev= 30
       0 2438.69      10 2436.92    29.9 2431.63    69.8  2418.9    89.7 2411.86
    99.6 2411.15   109.6 2407.84   159.4 2385.16   189.3 2373.66   199.3  2372.8
   219.2 2367.02   229.2 2366.26   248.4 2366.44   260.4 2366.49     299 2366.24
   338.8 2366.46   398.6 2368.38   438.5 2370.87   478.3 2376.34   498.2  2378.2
     568 2388.14     578 2390.61   597.9 2393.81   617.8 2399.02   627.8 2400.58
   697.6 2403.05   767.3 2410.32   817.1 2413.39   837.1 2415.85     867 2421.98
#Mann= 3 , 0 , 0
       0      .1       0   248.4    .045       0   260.4     .06       0
Bank Sta=248.4,260.4
XS Rating Curve= 0 ,0
Exp/Cntr=0.3,0.1

Type RM Length L Ch R = 1 ,346.6   ,243.5,253.4,263.4
XS GIS Cut Line= 3
     1895829.887       106235.96      1895760.49      106604.573
     1895848.757      107173.177
#Sta/Elev= 30
       0 2447.23    19.7 2445.25    59.2 2439.18   118.4 2442.95   157.9 2443.67
   197.4 2441.65   207.3 2442.14   256.6  2435.8   276.4  2432.2   296.1 2427.07
     306 2426.62   315.9 2424.73   335.6 2417.56   365.2 2403.24   394.9 2392.37
   414.8 2388.84   434.6 2381.61   474.3 2368.61   484.2 2366.78   501.2 2367.12
   513.2 2367.18   553.7 2367.74     643 2371.86   702.5 2375.35   742.2 2379.36
   791.8 2386.01   821.5 2389.05     891 2401.11   910.8 2403.13   950.5 2411.75
#Mann= 3 , 0 , 0
       0      .1       0   501.2    .045       0   513.2     .06       0
Bank Sta=501.2,513.2
XS Rating Curve= 0 ,0
Exp/Cntr=0.3,0.1

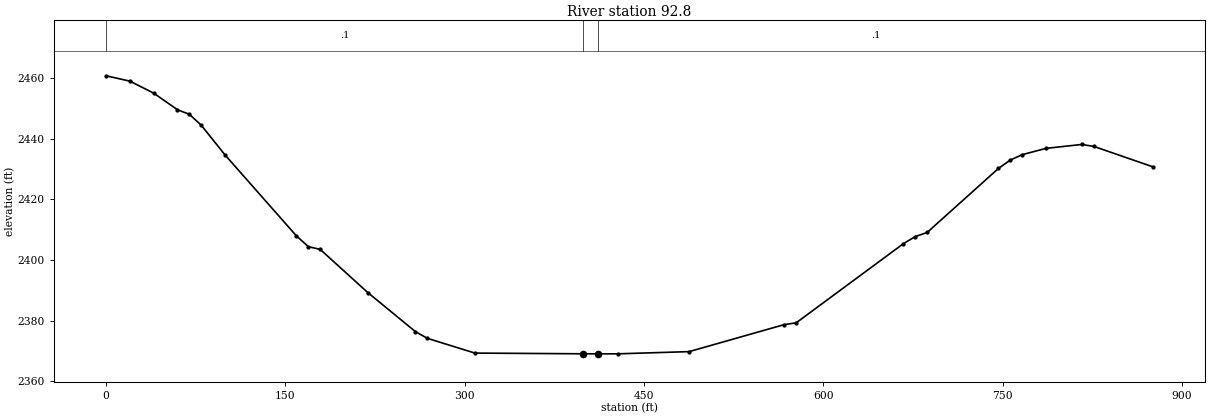
Type RM Length L Ch R = 1 ,92.8    ,95.4,92.8,90.3
XS GIS Cut Line= 2
     1895680.468      106370.694     1895401.676      107200.875
#Sta/Elev= 30
       0  2460.8    19.9 2459.03    39.8 2455.07    59.7 2449.59    69.7 2448.07
    79.6 2444.49    99.5 2434.66   159.2 2407.94   169.2 2404.38   179.1 2403.48
   218.9 2389.23   258.7 2376.35   268.7 2374.12   308.5 2369.25   399.3 2369.01
   411.3 2369.01   427.9    2369   487.6 2369.73   567.2 2378.65   577.2 2379.24
   666.8 2405.35   676.7  2407.7   686.7 2409.06   746.4 2430.22   756.3 2432.98
   766.3 2434.76   786.2 2436.84     816 2438.12     826  2437.5   875.7 2430.72
#Mann= 3 , 0 , 0
       0      .1       0   399.3    .045       0   411.3      .1       0
Bank Sta=399.3,411.3
XS Rating Curve= 0 ,0
Exp/Cntr=0.3,0.1

Chan Stop Cuts=-1
Use User Specified Reach Order=0
Composite Channel Slope=5